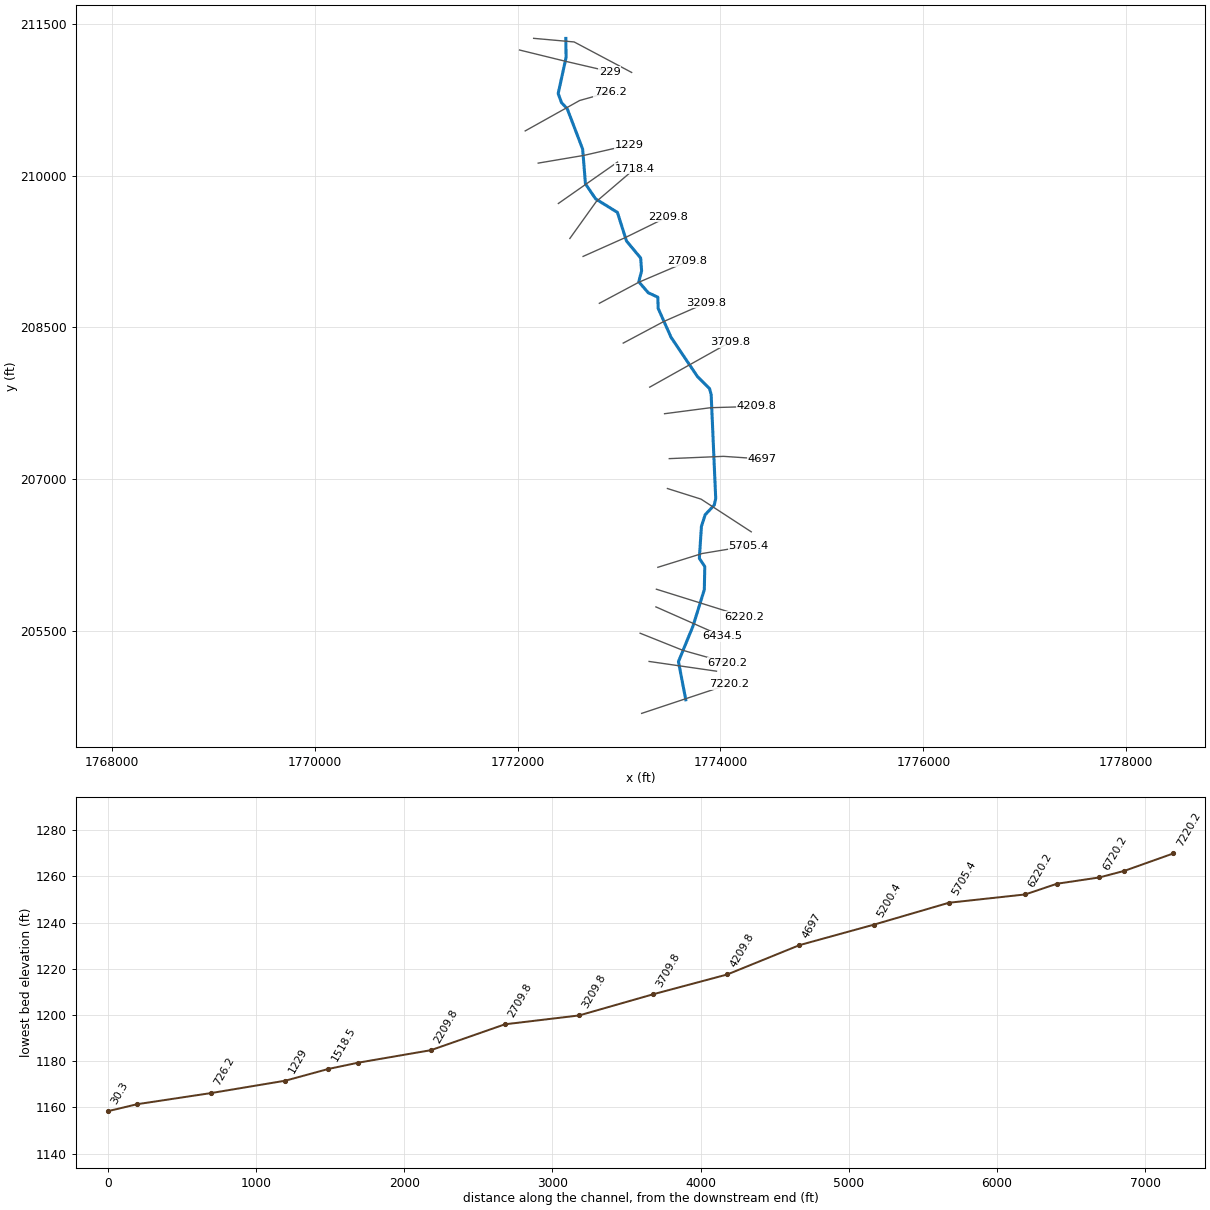
--- LitleCbCr2.prj (project) ---

Proj Title=LitleCbCr2
Current Plan=p01
Default Exp/Contr=0,0
English Units
Geom File=g01
Flow File=f01
Plan File=p01
BEGIN DESCRIPTION:
END DESCRIPTION:
DSS Export Rating Curves= 0
DSS Export Rating Curve Sorted= 0
DSS Export Volume Flow Curves= 0
DXF OffsetX= 0
DXF OffsetY= 0
DXF ScaleX= 0
DXF ScaleY= 0

--- LitleCbCr2.p01 (plan) ---

Plan Title=Floodplain
Program Version=4.00
Geom File=g01
Flow File=f01
K Sum by GR=0
Std Step Tol=0.01
Critical Tol=0.01
Num of Std Step Trials=20
Max Error Tol=0.3
Flow Tol Ratio=0.001
Split Flow NTrial=30
Split Flow Tol=0.02
Split Flow Ratio=0.02
Log Output Level=0
Friction Slope Method=1
Unsteady Friction Slope Method=2
Unsteady Bridges Friction Slope Method=1
Global Log Level=0
CheckData=False
Run HTab=0
Run UNet=0
Run PostProcess=0
UNET Theta=0
UNET Theta Warmup=0
UNET ZTol=0
UNET ZSATol=0
UNET MxIter=0
UNET MaxInSteps=0
UNET DtIC=0
UNET DtMin=0
UNET MaxCRTS=0
UNET WFStab=0
UNET SFStab=0
UNET WFX=0
UNET SFX=0
UNET DSS MLevel=0
UNET DZMax Abort=0
UNET Convert EG Bridges=0
UNET Use Existing IB Tables=0
UNET Froude Limit=0
UNET Froude Power=0
Write IC File=0
Echo Input=False
Echo Output=False
Write Detailed=0

--- LitleCbCr2.f01 (steady flow) ---

Flow Title=NFF Regression Equation
Program Version=4.00
Number of Profiles=1
Profile Names=P100yr
River Rch & RM=LitleCbCr2,Main      ,7220.2
584.8409
River Rch & RM=LitleCbCr2,Main      ,6889.9
584.9111
River Rch & RM=LitleCbCr2,Main      ,6889.9
774.1766
River Rch & RM=LitleCbCr2,Main      ,4209.8
844.7743
River Rch & RM=LitleCbCr2,Main      ,3209.8
905.2512
River Rch & RM=LitleCbCr2,Main      ,229
985.9317
Boundary for River Rch & Prof#=LitleCbCr2,Main      ,1
Up Type=0
Dn Type=3
Dn Slope=0.013146

--- LitleCbCr2.g01 (geometry) ---

Geom Title=USGS 10m DEM
Program Version=4.00

River Reach=LitleCbCr2      ,Main
Reach XY= 30
     1773658.391      204821.077      1773586.12      205197.861
      1773729.38      205548.561      1773841.17      205908.555
     1773845.848       206137.18     1773792.031       206217.95
     1773812.788      206534.492     1773849.911      206649.322
     1773939.054      206744.018      1773953.53      206808.125
     1773908.724      207835.908      1773892.87      207894.501
     1773773.616      208013.754     1773514.393      208399.813
     1773386.216      208687.225     1773382.769      208798.206
     1773289.021      208841.634     1773195.273      208949.858
     1773222.846      209057.392     1773213.885      209184.228
     1773073.952      209353.113     1772984.339      209635.736
     1772769.754       209769.11     1772669.429      209917.868
     1772641.745      210260.954     1772490.093      210658.694
     1772433.569      210720.044     1772400.481      210809.657
     1772478.528      211166.824     1772475.852      211354.179

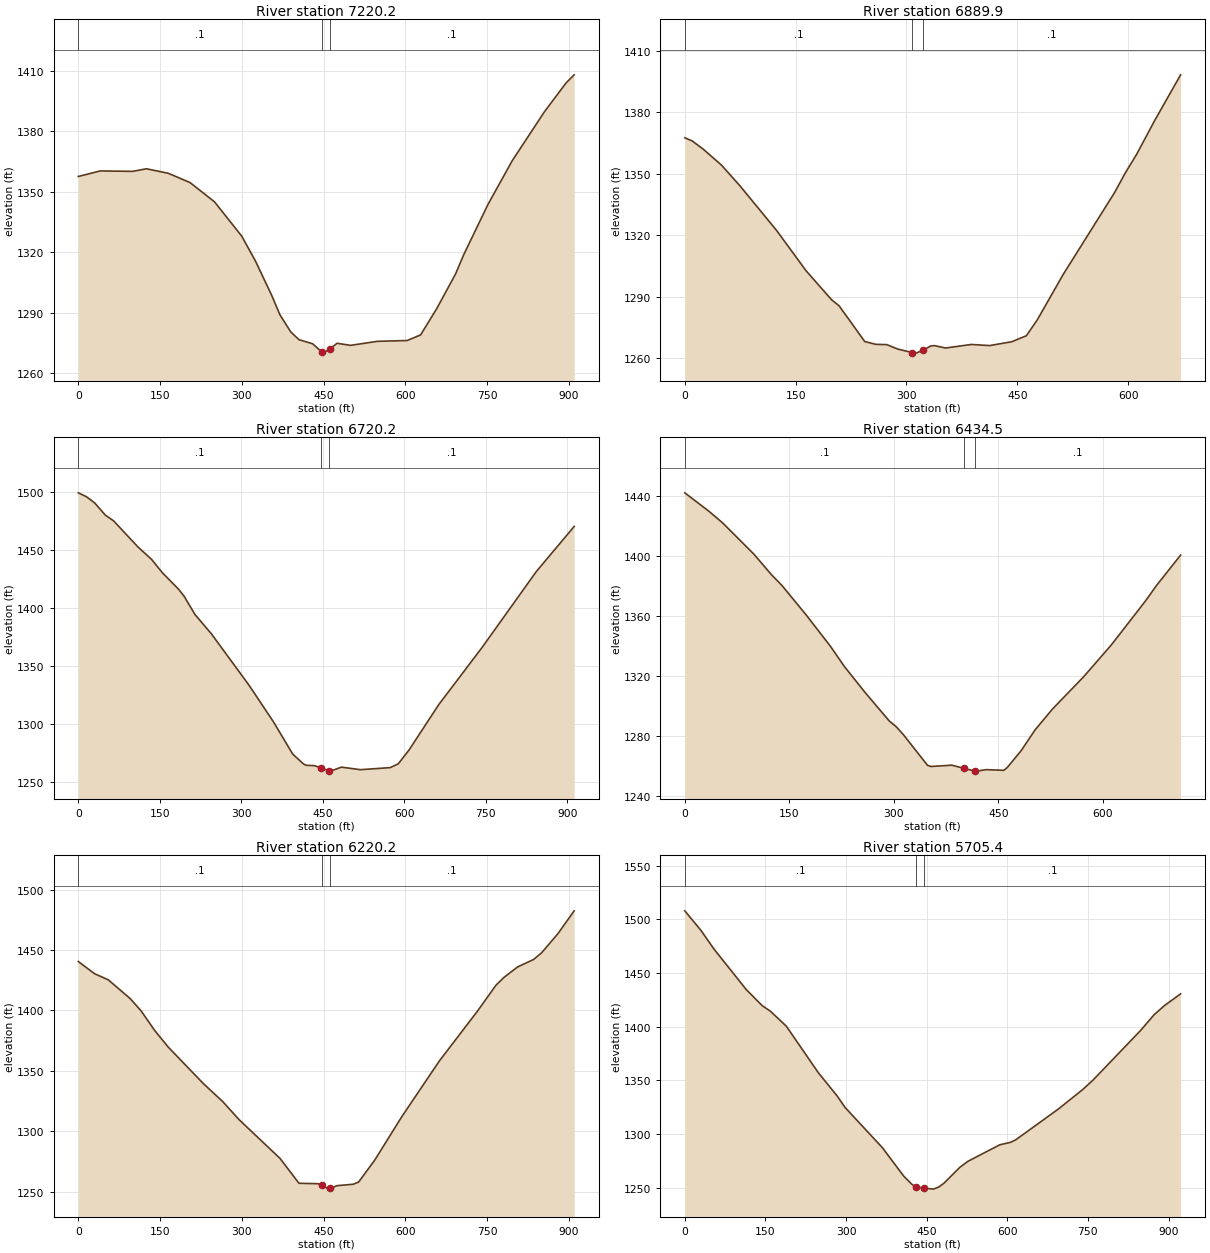
Type RM Length L Ch R = 1 ,7220.2  ,341.8,330.3,319.8
XS GIS Cut Line= 3
     1773223.554      204686.756      1773655.23      204830.565
     1774086.906      204974.373
#Sta/Elev= 30
       0 1357.54      40 1360.28     100 1360.08     125 1361.36     165 1359.13
     205 1354.53     250 1344.95     300  1327.9     325 1315.65     355 1298.51
     370 1288.94     390  1280.4     405 1276.59     430 1274.56   447.5 1270.36
     450 1269.92   462.5 1272.13   474.8  1274.8   499.5 1273.78     549 1275.77
   603.4 1276.17   628.1 1278.94   657.8 1291.99   692.4 1309.22   707.2 1318.66
   751.7  1343.6   796.2  1365.3   855.6  1389.7   895.2 1403.94     910 1407.96
#Mann= 3 , 0 , 0
       0      .1       0   447.5    .045       0   462.5      .1       0
#XS Ineff= 2 , 0
                          477.41         1274.56
Permanent Ineff=
       F       F
Bank Sta=447.5,462.5
XS Rating Curve= 0 ,0
Exp/Cntr=0.3,0.1

Type RM Length L Ch R = 1 ,6889.9  ,175.1,169.7,165.5
XS GIS Cut Line= 2
     1773296.943      205199.681     1773961.129      205103.519
#Sta/Elev= 30
       0 1367.46     9.9 1365.94    24.9 1361.93    49.7  1354.1    74.6 1344.04
   124.3 1322.22     164 1302.64   198.8 1288.37   208.8 1285.49   243.6 1268.03
   258.5 1266.67   273.4 1266.53   288.3 1264.35     308 1262.66   313.2 1262.38
     323 1263.94   333.1  1265.9     338 1266.04     353 1264.88   387.8 1266.61
   412.6 1266.06   442.4 1267.93   462.3 1270.85   477.2 1278.68     512 1300.67
   581.6 1340.66   596.5 1350.48   611.5 1359.35   636.3 1376.07   671.1 1398.18
#Mann= 3 , 0 , 0
       0      .1       0     308    .045       0     323      .1       0
Bank Sta=308,323
XS Rating Curve= 0 ,0
Exp/Cntr=0.3,0.1

Type RM Length L Ch R = 1 ,6720.2  ,286.5,285.7,282.5
XS GIS Cut Line= 3
     1773208.307      205478.663     1773630.069      205309.421
     1774070.861      205184.664
#Sta/Elev= 30
       0 1498.86      15 1495.49      30 1490.19    49.9  1479.6    64.9 1474.77
   109.9 1452.23   134.8 1441.64   154.8 1430.08   184.8 1415.82   194.8 1409.85
   214.7 1394.22   244.7 1377.72   314.6 1333.12   359.6 1301.59   394.5 1274.21
   414.5 1265.66   419.5 1264.52   434.5 1264.23     447 1262.26     462 1259.67
   464.4 1259.51   484.3 1262.94   519.2 1260.75     574 1262.53   588.9 1265.82
   608.8 1277.76   663.6 1316.85   743.3 1365.98   842.8 1431.08   912.6 1469.93
#Mann= 3 , 0 , 0
       0      .1       0     447    .045       0     462      .1       0
Bank Sta=447,462
XS Rating Curve= 0 ,0
Exp/Cntr=0.3,0.1

Type RM Length L Ch R = 1 ,6434.5  ,211.8,214.3,216.9
XS GIS Cut Line= 2
     1773364.032      205738.634     1774014.801      205450.149
#Sta/Elev= 30
       0  1441.8    34.8  1429.5    54.8 1421.61    99.6 1400.84   124.4 1387.37
   139.4 1380.26   174.2 1360.65   209.1 1339.77     229 1326.41   258.8  1309.1
   293.7 1290.05   303.6 1286.27   313.6 1281.16   348.5 1260.63   353.4 1259.88
   383.3 1260.74     401 1258.62     416 1256.86   418.2 1256.79   433.1 1257.78
     458 1257.32     463 1259.24   482.9 1270.41   502.8 1284.16   527.7    1298
   572.5 1319.48   612.3 1340.68   662.1 1370.37     677  1380.1   711.8  1400.4
#Mann= 3 , 0 , 0
       0      .1       0     401    .045       0     416      .1       0
Bank Sta=401,416
XS Rating Curve= 0 ,0
Exp/Cntr=0.3,0.1

Type RM Length L Ch R = 1 ,6220.2  ,500.4,514.8,528.1
XS GIS Cut Line= 3
     1773368.764      205913.299     1773802.922      205777.165
     1774237.079      205641.032
#Sta/Elev= 30
       0  1440.5      30 1430.37      55 1425.36      95 1409.92     115 1399.78
     140 1383.55     165 1369.71     230 1339.27     265 1324.62     295 1309.68
     370 1277.66     405    1257     440 1256.66   447.5 1255.17     460 1252.16
   462.5 1252.68   474.8 1255.03   504.5 1256.19   514.4    1258     544 1276.15
   593.5    1312   662.7 1358.28     732 1399.13   766.6 1420.94   781.4 1427.45
   806.1 1435.98   835.8 1442.27   850.6 1447.91   880.3 1463.61     910 1482.46
#Mann= 3 , 0 , 0
       0      .1       0   447.5    .045       0   462.5      .1       0
Bank Sta=447.5,462.5
XS Rating Curve= 0 ,0
Exp/Cntr=0.3,0.1

Type RM Length L Ch R = 1 ,5705.4  ,526,505,485.3
XS GIS Cut Line= 3
     1773383.093      206129.811     1773819.703      206265.865
     1774278.653      206341.974
#Sta/Elev= 30
       0 1507.88    29.8 1489.83    54.7 1471.99   114.3 1434.54   144.2 1419.44
   159.1 1414.44   188.9 1400.39   248.5 1356.99   283.3 1335.49   298.2 1324.68
   367.8 1287.06   407.6 1260.52   422.5 1253.07   429.9 1250.62   444.9 1249.59
   462.3 1248.56   472.2 1250.44   482.1 1254.03   511.8  1268.9   526.6 1274.42
     586 1289.85   605.8 1292.16   615.7  1294.5   694.9 1323.14   739.4 1340.96
   759.2 1349.99   848.3 1396.54     873 1410.96   892.8 1419.74   922.5 1430.54
#Mann= 3 , 0 , 0
       0      .1       0   429.9    .045       0   444.9      .1       0
Bank Sta=429.9,444.9
XS Rating Curve= 0 ,0
Exp/Cntr=0.3,0.1

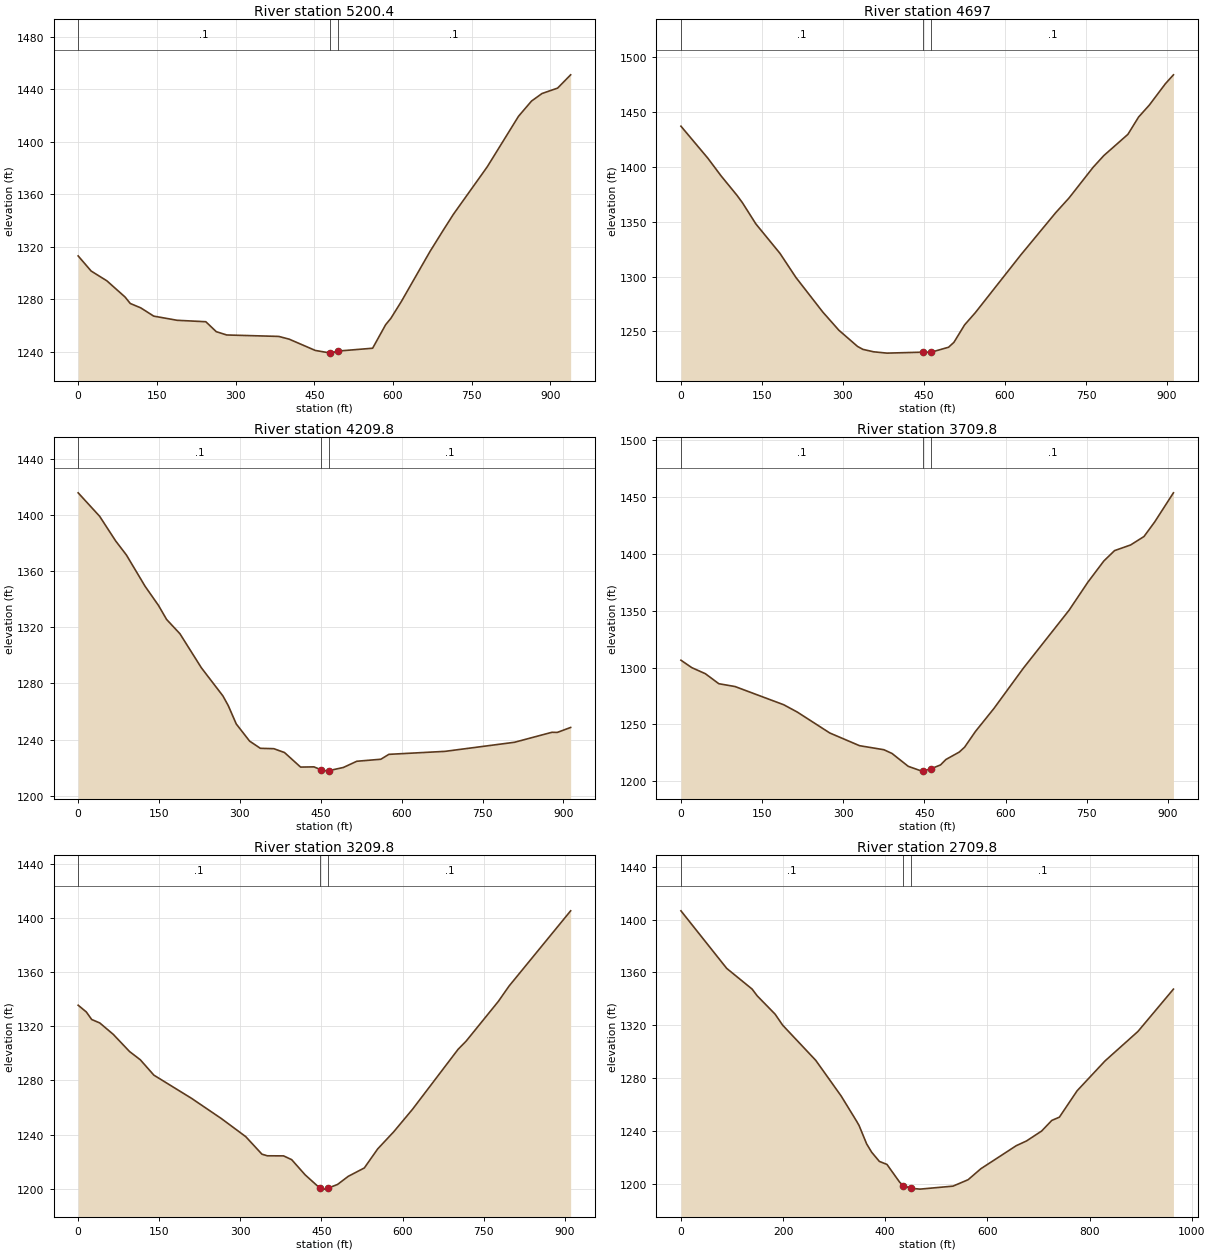
Type RM Length L Ch R = 1 ,5200.4  ,489.2,503.4,517.5
XS GIS Cut Line= 3
     1773477.626      206907.959      1773809.06      206803.121
     1774303.961      206480.123
#Sta/Elev= 30
       0 1313.05    24.8 1301.54    54.6 1294.15    89.4 1281.78    99.3 1276.87
   119.2 1273.56     144 1267.26   188.7 1264.08   243.3 1262.99   263.2 1255.43
   283.1 1252.91   382.4 1251.81   402.2 1249.72   451.9 1241.15   479.5 1239.24
   481.7  1239.1   494.5 1240.64   561.2 1242.83     586 1260.72   595.9 1265.53
   615.8 1278.28   670.4 1316.35   695.2 1332.24   715.1  1344.7   779.7 1380.89
   839.3 1419.34   864.1 1430.91     884 1436.62   913.8 1440.76   938.6 1450.85
#Mann= 3 , 0 , 0
       0      .1       0   479.5    .045       0   494.5      .1       0
Bank Sta=479.5,494.5
XS Rating Curve= 0 ,0
Exp/Cntr=0.3,0.1

Type RM Length L Ch R = 1 ,4697    ,485.2,487.2,486.9
XS GIS Cut Line= 3
     1773495.823      207203.226     1774030.455      207225.786
     1774406.298      207200.464
#Sta/Elev= 30
       0 1436.94    49.6  1407.9    74.3 1391.68     104 1373.81     114  1367.1
   138.7 1347.92   183.3 1321.12     213 1299.06   262.6 1267.66   292.3 1251.11
     327  1236.3   336.9 1233.64   356.7 1231.42   381.5 1230.21   448.2 1231.09
   463.2 1231.05   495.5 1235.58   505.4 1240.05   525.2 1255.96     545 1267.05
   629.3 1319.71   693.7 1358.06   718.5 1371.52   763.1 1399.48   782.9 1410.15
   827.5  1429.5   847.4 1445.33   867.2 1456.18   896.9 1475.59   911.8 1483.73
#Mann= 3 , 0 , 0
       0      .1       0   448.2    .045       0   463.2      .1       0
Bank Sta=448.2,463.2
XS Rating Curve= 0 ,0
Exp/Cntr=0.3,0.1

Type RM Length L Ch R = 1 ,4209.8  ,491.1,500,511.2
XS GIS Cut Line= 3
     1773449.324      207646.951     1773902.637       207706.29
     1774358.538      207719.656
#Sta/Elev= 30
       0 1415.92    39.8 1399.21    69.6 1381.59    89.4 1371.65   124.2 1349.25
   149.1 1335.56     164 1325.65   188.8 1315.42   228.6 1291.12   268.4 1271.15
   278.3 1264.27   293.2 1251.13     318 1238.89   337.9 1233.77   362.8 1233.51
   382.6 1230.78   412.5 1220.39   437.3 1220.55   449.7 1218.58   462.1 1217.51
   464.7 1217.83   491.9 1220.13   516.7 1224.54   561.3 1225.98   576.2 1229.47
   680.3  1231.6   809.2 1238.08   878.6  1245.2   888.5 1245.11   913.3 1248.64
#Mann= 3 , 0 , 0
       0      .1       0   449.7    .045       0   464.7      .1       0
Bank Sta=449.7,464.7
XS Rating Curve= 0 ,0
Exp/Cntr=0.3,0.1

Type RM Length L Ch R = 1 ,3709.8  ,500.5,500,497.8
XS GIS Cut Line= 3
     1773302.721      207909.396     1773699.546      208132.006
     1774096.371      208354.616
#Sta/Elev= 30
       0 1306.57      20 1300.03      45 1294.72      70 1285.88     100 1283.39
     190 1267.35     215 1260.92     275 1242.52     330 1231.33     375 1227.78
     390 1224.49     420 1213.17     445 1208.94   447.5 1209.06   462.5 1211.07
   479.7 1214.43   489.6 1219.18   514.4 1225.75   524.2 1230.05     544 1243.74
   578.6 1264.26     633 1299.73   717.1 1350.51   751.7 1375.11   781.4  1393.9
   801.2 1403.03   830.9 1408.01   855.6 1415.44   875.4 1428.29     910  1453.9
#Mann= 3 , 0 , 0
       0      .1       0   447.5    .045       0   462.5      .1       0
Bank Sta=447.5,462.5
XS Rating Curve= 0 ,0
Exp/Cntr=0.3,0.1

Type RM Length L Ch R = 1 ,3209.8  ,499.8,500,499.9
XS GIS Cut Line= 3
     1773041.929      208344.623     1773443.286      208558.695
     1773860.715      208742.138
#Sta/Elev= 30
       0 1335.56      15 1330.62      25 1325.02      40 1322.47      65 1314.02
      95 1301.38     115 1295.25     140 1283.94   209.9 1266.75   264.9 1251.85
   309.9 1238.54   339.9 1225.56   349.9 1224.38   379.9 1224.32   394.9 1221.52
   419.9 1210.27   447.4 1200.39   454.9 1199.77   462.4 1200.53   479.7 1203.22
   499.5 1209.22   529.2 1215.39     554 1229.49   583.7 1242.15   618.4 1258.75
   702.7 1303.03   717.6 1309.09     777 1338.34   796.8 1349.65   910.8 1405.26
#Mann= 3 , 0 , 0
       0      .1       0   447.4    .045       0   462.4      .1       0
Bank Sta=447.4,462.4
XS Rating Curve= 0 ,0
Exp/Cntr=0.3,0.1

Type RM Length L Ch R = 1 ,2709.8  ,501.9,500,500.9
XS GIS Cut Line= 3
      1772806.37      208737.643     1773197.277      208946.587
     1773676.444      209151.247
#Sta/Elev= 30
       0 1406.62    89.6 1363.05   139.4 1347.36   149.4 1342.22   184.3 1328.43
   199.2 1320.04     264 1293.42   313.8 1266.38   343.6  1247.6   348.6 1244.27
   363.6 1230.19   373.5 1223.86   388.5 1216.93   403.4 1214.64   428.3 1201.16
   435.7 1198.57   450.7 1196.57   468.1 1195.94   532.6  1198.2   562.3 1203.07
   587.2 1211.37   656.6 1228.84   676.5 1232.38   706.2  1239.9   726.1 1247.94
     741 1250.42   775.7 1270.38   830.3 1292.97   894.8 1315.29   964.3 1347.34
#Mann= 3 , 0 , 0
       0      .1       0   435.7    .045       0   450.7      .1       0
Bank Sta=435.7,450.7
XS Rating Curve= 0 ,0
Exp/Cntr=0.3,0.1

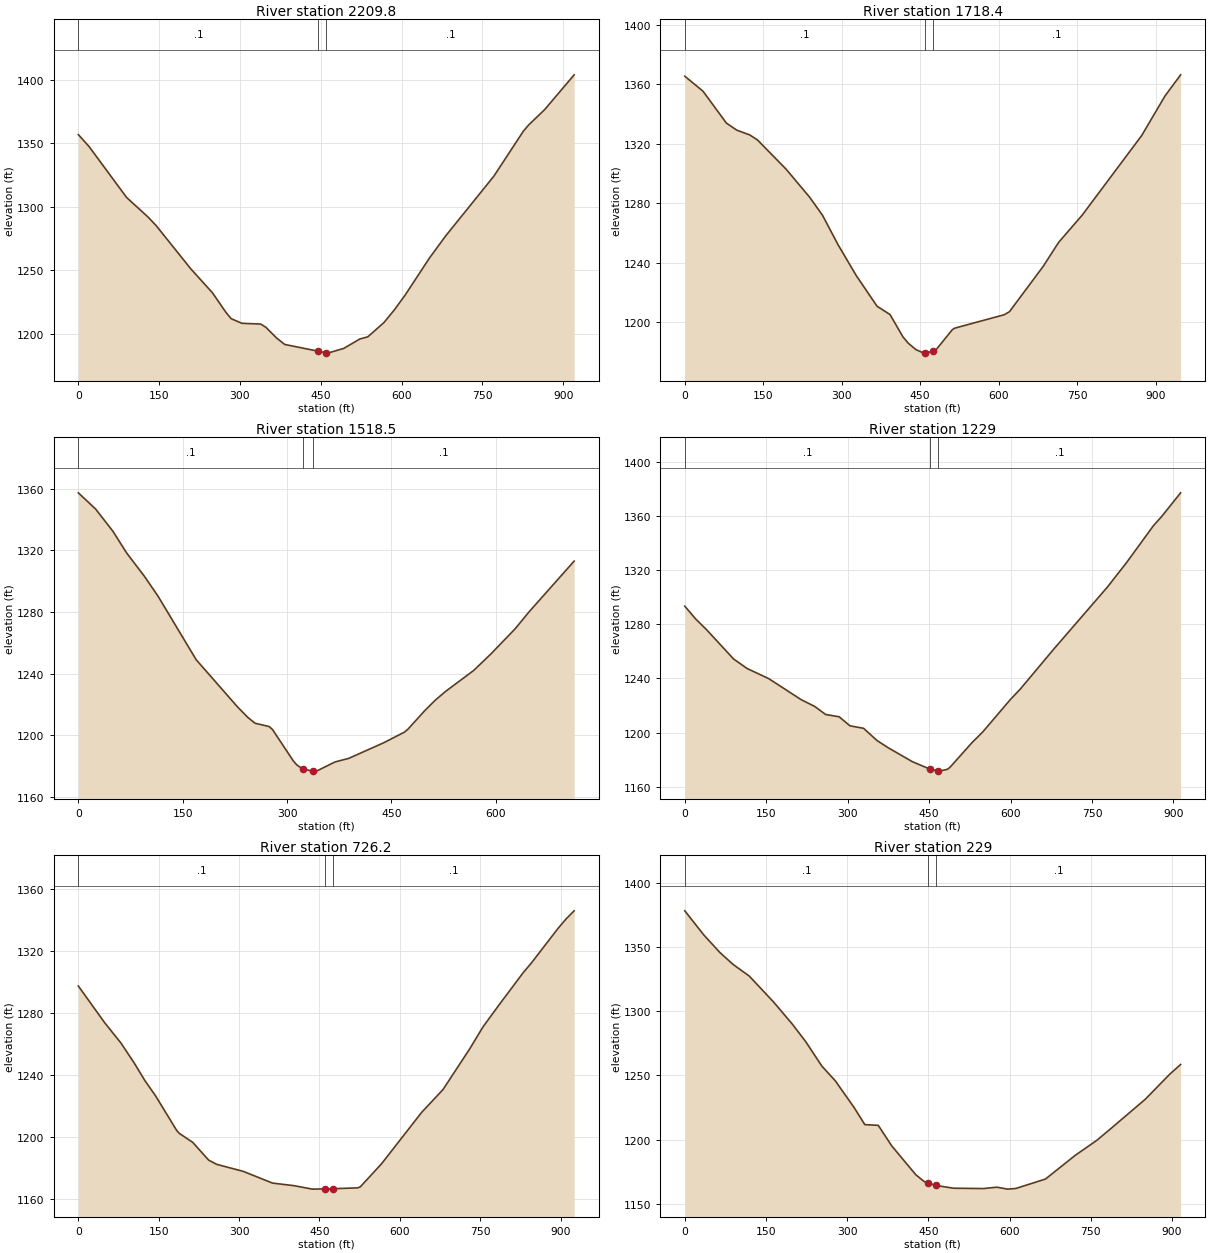
Type RM Length L Ch R = 1 ,2209.8  ,484,491.4,497.2
XS GIS Cut Line= 3
     1772646.051      209200.797     1773059.428        209385.6
     1773478.999      209591.659
#Sta/Elev= 30
       0 1357.02    19.9 1347.61    89.6 1307.44   129.4    1292   144.3 1285.32
     209 1251.03   248.8 1232.37   273.7 1217.01   283.6  1211.9   303.5 1208.25
   338.4 1207.65   348.3 1205.03   368.2 1196.55   383.1 1191.56   445.3 1186.23
   460.3 1184.81   462.8 1184.73   492.6 1188.45   522.4 1195.85   537.3  1197.6
   567.2 1208.84   587.1 1219.14     607 1230.78   651.7 1259.72   681.6 1277.05
   771.1 1324.19   825.8 1359.59   835.7 1364.57   865.5 1376.72   920.2 1404.12
#Mann= 3 , 0 , 0
       0      .1       0   445.3    .045       0   460.3      .1       0
Bank Sta=445.3,460.3
XS Rating Curve= 0 ,0
Exp/Cntr=0.3,0.1

Type RM Length L Ch R = 1 ,1718.4  ,202.8,200,197.9
XS GIS Cut Line= 3
     1772515.639      209378.156     1772775.413      209741.837
     1773155.668      210067.623
#Sta/Elev= 30
       0 1365.35    34.8 1355.28    79.4 1333.89    99.3 1329.11   124.2 1325.89
     139  1322.5   193.7 1302.87   238.4 1284.16   263.2 1271.94     293 1252.09
   327.8 1231.37   367.5 1210.81   392.3 1205.23   417.1 1190.16   427.1 1185.98
     442 1181.63   456.8 1179.31   459.7 1179.42   474.7 1180.52   481.6 1182.14
   511.4 1195.11   516.3 1196.12   610.5  1205.1   620.4 1207.09   684.9 1237.53
   714.6 1253.74   759.3  1271.9   873.3 1325.49   917.9  1352.1   947.7 1366.27
#Mann= 3 , 0 , 0
       0      .1       0   459.7    .045       0   474.7      .1       0
Bank Sta=459.7,474.7
XS Rating Curve= 0 ,0
Exp/Cntr=0.3,0.1

Type RM Length L Ch R = 1 ,1518.5  ,299.5,289.4,280.7
XS GIS Cut Line= 2
     1772402.415      209723.754     1772986.094         210133.
#Sta/Elev= 30
       0 1357.48    24.9 1346.94    49.8 1332.44    69.8 1318.19    94.7 1303.43
   114.7 1290.24   169.5 1248.99   229.3 1218.14   244.3 1211.28   254.2 1207.72
   274.2 1205.61   279.2 1203.65   309.1 1183.25   314.1 1180.67   322.7 1177.94
   337.7 1176.61     344 1176.96   368.9 1182.54   388.8  1184.9   438.7 1194.97
   468.6 1201.88   473.6  1203.7   498.5 1216.12   513.5 1222.83   528.4 1228.55
   568.3 1241.98   593.2 1252.77   628.1 1269.13     648 1280.09   712.9 1313.12
#Mann= 3 , 0 , 0
       0      .1       0   322.7    .045       0   337.7      .1       0
Bank Sta=322.7,337.7
XS Rating Curve= 0 ,0
Exp/Cntr=0.3,0.1

Type RM Length L Ch R = 1 ,1229    ,495,502.9,509.4
XS GIS Cut Line= 3
     1772203.561      210122.523      1772655.96      210199.171
     1773098.713      210301.043
#Sta/Elev= 30
       0 1293.29      20 1283.84    39.9 1276.01    89.8 1254.34   114.7  1247.3
   154.6  1239.8   214.5 1224.24   239.4 1219.26   259.4 1213.33   284.3 1211.65
   304.2 1204.97   329.2 1203.16   354.1 1194.12   374.1 1188.91     419 1178.54
   451.3 1173.04   466.3 1171.57   468.8 1171.54   483.8  1172.9   488.8 1174.52
   528.7 1192.46   548.7 1200.44   598.6  1223.9   618.6 1232.42   678.5  1261.1
   778.4  1307.4   813.3 1325.27   863.2 1352.71   878.2  1359.4   913.2 1376.93
#Mann= 3 , 0 , 0
       0      .1       0   451.3    .045       0   466.3      .1       0
Bank Sta=451.3,466.3
XS Rating Curve= 0 ,0
Exp/Cntr=0.3,0.1

Type RM Length L Ch R = 1 ,726.2   ,514.3,497.1,480.3
XS GIS Cut Line= 3
      1772075.53      210440.605     1772612.629      210741.279
     1772910.774      210824.772
#Sta/Elev= 30
       0 1297.31    49.6 1273.41    79.4 1260.56   104.2 1247.65   124.1 1236.29
     144 1226.46   183.7 1203.96   188.6 1202.12   213.4 1196.38   243.2 1184.88
   258.1 1182.18   307.8 1177.62   362.4 1170.05   402.1 1168.41   436.8 1166.16
   459.4 1166.31   474.4 1166.42   521.2 1166.98   526.2 1167.65   565.9 1182.57
   640.5 1215.67   680.4 1230.42   730.4 1256.78   755.4 1271.09   785.3 1285.22
   830.3 1306.02   845.2 1312.09   895.2 1334.54   910.2 1340.65   925.2 1345.86
#Mann= 3 , 0 , 0
       0      .1       0   459.4    .045       0   474.4      .1       0
Bank Sta=459.4,474.4
XS Rating Curve= 0 ,0
Exp/Cntr=0.3,0.1

Type RM Length L Ch R = 1 ,229     ,195.9,198.7,201.7
XS GIS Cut Line= 3
     1772019.883      211239.736     1772463.193      211130.741
     1772910.509      211026.359
#Sta/Elev= 30
       0 1378.31    34.7 1359.71    64.5 1345.95    89.3 1336.48   119.1 1327.44
   163.8 1307.32   198.5 1290.04   223.3 1276.36   253.1  1257.3   277.9 1245.84
   312.6 1225.06   332.5 1211.64   357.3  1211.1   382.1 1195.15   426.7 1172.56
   441.6 1167.46     449 1166.22     464 1164.24   496.4 1162.07   551.4 1161.81
   576.3 1162.87   596.3 1161.36   611.3 1161.86   666.2 1169.22   721.1 1187.67
   761.1 1199.43     786 1208.22   850.9 1231.57   895.9 1251.04   915.8 1258.53
#Mann= 3 , 0 , 0
       0      .1       0     449    .045       0     464      .1       0
Bank Sta=449,464
XS Rating Curve= 0 ,0
Exp/Cntr=0.3,0.1

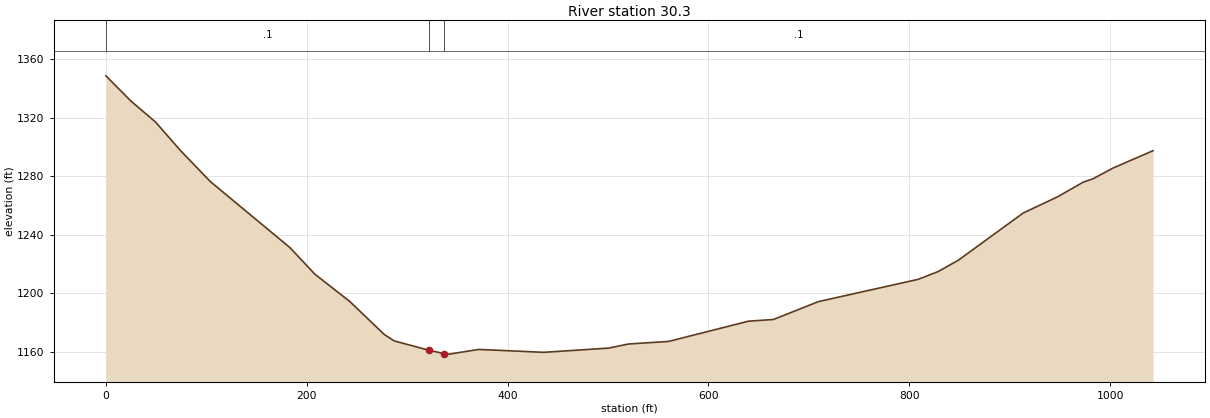
Type RM Length L Ch R = 1 ,30.3    ,27.6,30.3,39.5
XS GIS Cut Line= 3
     1772158.656      211355.148     1772558.212      211319.367
     1773124.746       211018.21
#Sta/Elev= 30
       0 1348.81    24.8 1331.62    49.5 1317.13    74.3 1297.66     104 1276.43
   183.2 1231.27     208 1213.11   242.7 1194.45   277.3 1171.71   287.2 1167.34
   321.5 1161.01   336.5 1158.72   341.7 1158.31   371.4 1161.52     436 1159.54
   500.6 1162.43   520.5 1165.25   560.3 1166.99   639.9 1180.86   664.8 1182.03
   709.5 1194.24     809 1209.51   828.9 1214.87   848.8 1222.55   913.4 1254.85
   948.3  1266.2   973.1 1275.97   983.1 1278.37    1003 1285.68  1042.8 1297.58
#Mann= 3 , 0 , 0
       0      .1       0   321.5    .045       0   336.5      .1       0
Bank Sta=321.5,336.5
XS Rating Curve= 0 ,0
Exp/Cntr=0.3,0.1

Chan Stop Cuts=-1
Use User Specified Reach Order=0